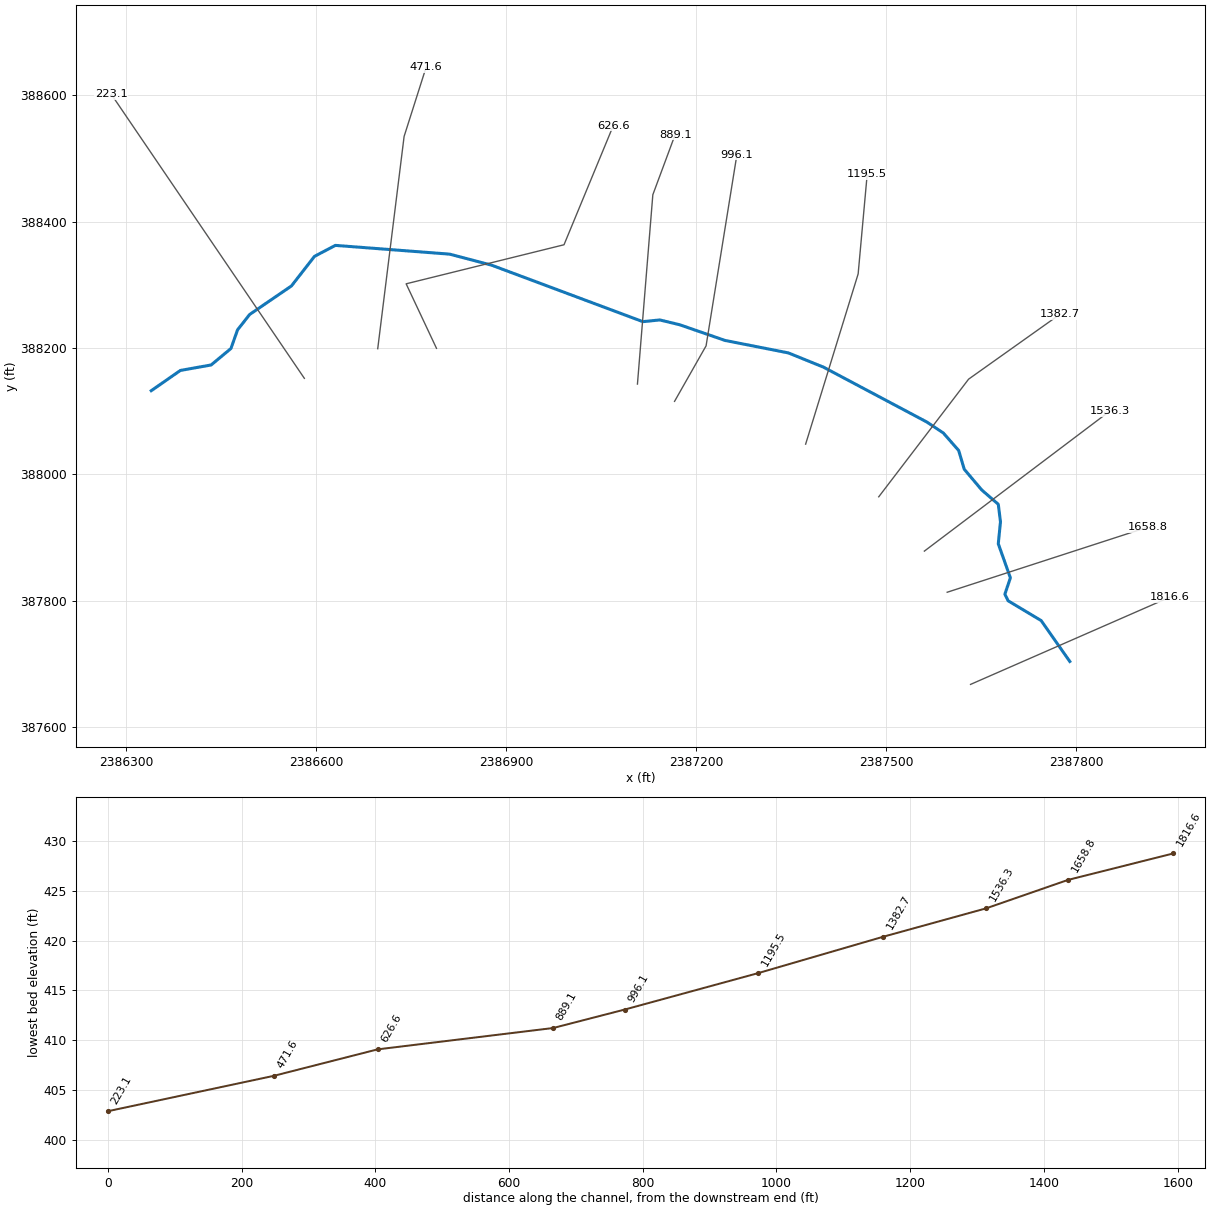
--- BACKTRIB4.prj (project) ---

Proj Title=BACKTRIB4
Current Plan=p01
Default Exp/Contr=0,0
English Units
Geom File=g01
Flow File=f01
Plan File=p01
BEGIN DESCRIPTION:
END DESCRIPTION:
DSS Export Rating Curves= 0
DSS Export Rating Curve Sorted= 0
DSS Export Volume Flow Curves= 0
DXF OffsetX= 0
DXF OffsetY= 0
DXF ScaleX= 0
DXF ScaleY= 0

--- BACKTRIB4.p01 (plan) ---

Plan Title=Floodplain
Program Version=4.00
Geom File=g01
Flow File=f01
K Sum by GR=0
Std Step Tol=0.01
Critical Tol=0.01
Num of Std Step Trials=20
Max Error Tol=0.3
Flow Tol Ratio=0.001
Split Flow NTrial=30
Split Flow Tol=0.02
Split Flow Ratio=0.02
Log Output Level=0
Friction Slope Method=1
Unsteady Friction Slope Method=2
Unsteady Bridges Friction Slope Method=1
Global Log Level=0
CheckData=False
Run HTab=0
Run UNet=0
Run PostProcess=0
UNET Theta=0
UNET Theta Warmup=0
UNET ZTol=0
UNET ZSATol=0
UNET MxIter=0
UNET MaxInSteps=0
UNET DtIC=0
UNET DtMin=0
UNET MaxCRTS=0
UNET WFStab=0
UNET SFStab=0
UNET WFX=0
UNET SFX=0
UNET DSS MLevel=0
UNET DZMax Abort=0
UNET Convert EG Bridges=0
UNET Use Existing IB Tables=0
UNET Froude Limit=0
UNET Froude Power=0
Write IC File=0
Echo Input=False
Echo Output=False
Write Detailed=0

--- BACKTRIB4.f01 (steady flow) ---

Flow Title=NFF Regression Equation
Program Version=4.00
Number of Profiles=1
Profile Names=P100yr
River Rch & RM=BACKTRIB4,Main      ,1816.6
562.8008
River Rch & RM=BACKTRIB4,Main      ,471.6
575.3509
River Rch & RM=BACKTRIB4,Main      ,223.1
576.0279
Boundary for River Rch & Prof#=BACKTRIB4,Main      ,1
Up Type=0
Dn Type=3
Dn Slope=0.013172

--- BACKTRIB4.g01 (geometry) ---

Geom Title=USGS 10m DEM
Program Version=4.10

River Reach=BACKTRIB4       ,Main
Reach XY= 30
     2387790.326      387703.877     2387745.056      387768.624
     2387692.973      387799.874     2387687.765      387810.291
     2387696.445      387836.332     2387677.348      387890.152
      2387680.82      387924.874     2387677.348      387952.652
     2387651.306      387975.221     2387623.528      388008.207
     2387614.848      388037.721     2387590.542      388065.499
     2387564.501       388082.86     2387401.306      388169.666
      2387345.75      388192.235     2387245.795       388211.95
      2387174.05      388236.819       2387142.8      388244.372
     2387116.015      388241.669     2386877.045       388331.09
     2386811.028      388348.485     2386630.473      388362.374
     2386597.487      388345.013     2386561.028      388298.138
     2386495.056      388252.999     2386475.959      388228.693
     2386465.542      388199.179     2386434.292      388173.138
     2386385.681      388164.457     2386339.698      388132.423

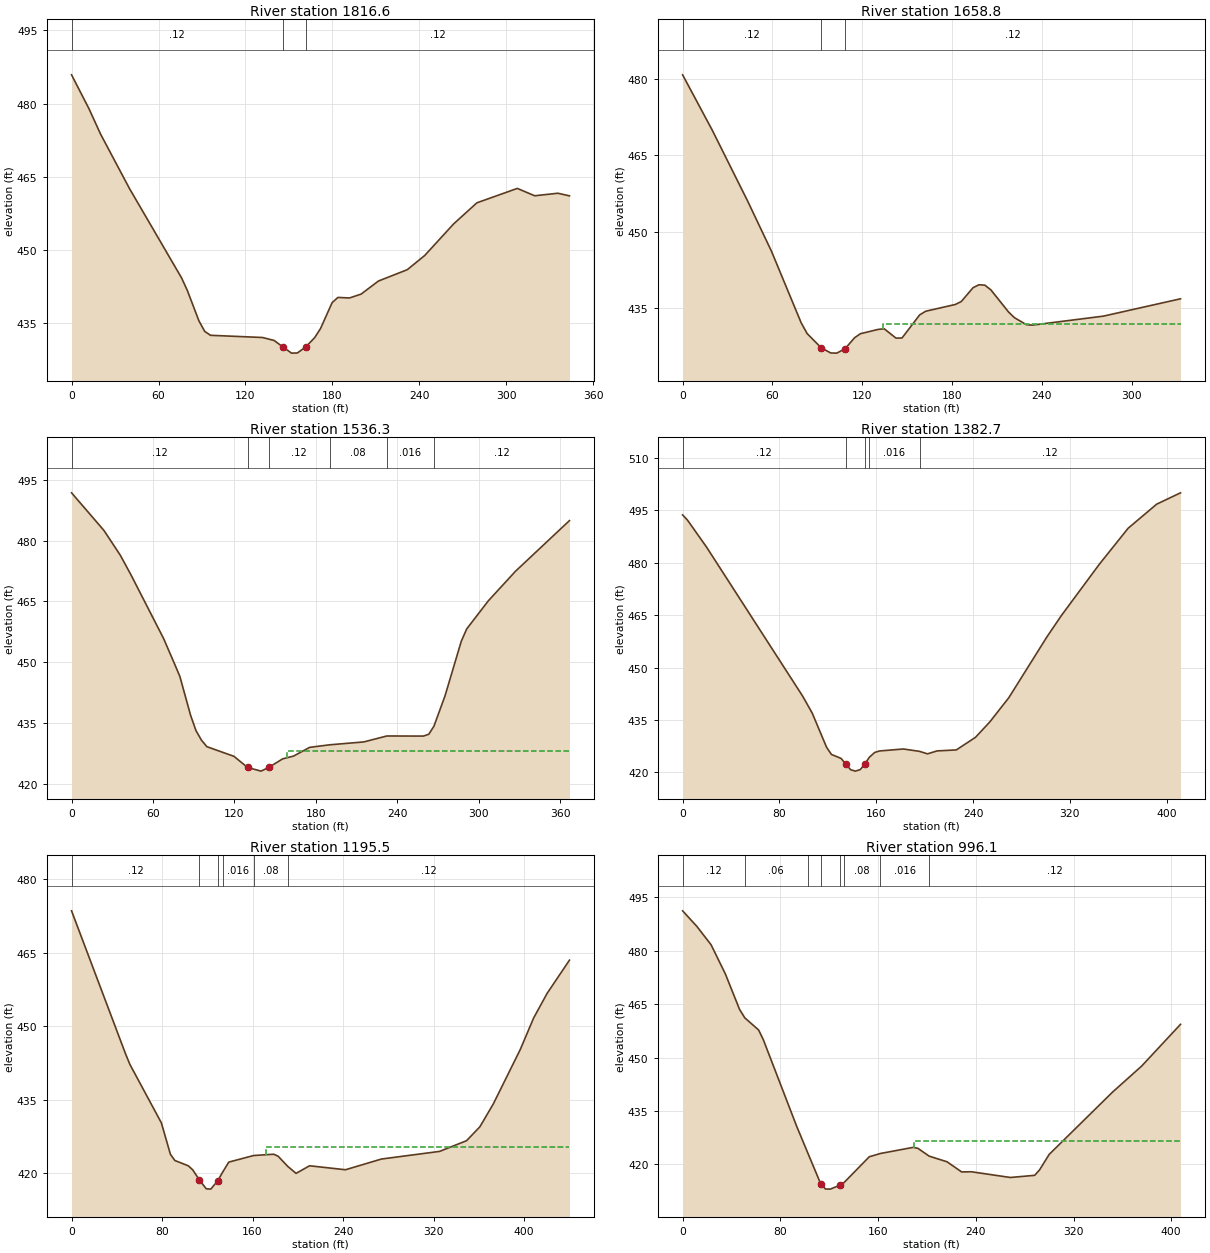
Type RM Length L Ch R = 1 ,1816.6  ,160.9,157.8,152.6
XS GIS Cut Line= 2
     2387633.534      387667.614     2387948.204      387805.635
#Sta/Elev= 30
       0  485.89      12  478.94      20  473.73      40  462.52    75.9  444.19
    79.9   441.6    87.9  435.36    91.9  433.19    95.9  432.39   131.8  431.94
   139.8  431.33  145.92 429.981   151.8  428.73   155.8  428.76  161.59429.9933
   167.8  431.92   171.8  433.77   179.8  439.09   183.8  440.17   191.8  440.06
   199.8  440.85   211.8  443.54   231.7  445.87   243.7  448.78   263.7  455.28
   279.7   459.6   307.6  462.56   319.6  461.05   335.6  461.57   343.6  461.03
#Mann= 3 ,-1 , 0
       0     .12       0  145.92    .045       0  161.59     .12       0
Bank Sta=145.92,161.59
XS Rating Curve= 0 ,0
Exp/Cntr=0.3,0.1

Type RM Length L Ch R = 1 ,1658.8  ,114.4,122.5,130.6
XS GIS Cut Line= 2
     2387596.641      387813.447     2387913.048      387916.312
#Sta/Elev= 30
       0  480.83    19.8  469.94    43.6   455.9    59.4   446.1    79.2  432.05
    83.2  429.92   92.66427.1026      99   426.1     103  426.07  108.52 426.923
   114.9  429.09   118.8  429.89   130.7  430.74   134.7  430.86   142.6  429.02
   146.6  429.05   158.4  433.59   162.4  434.31   182.2  435.64   186.2  436.22
   194.1  438.95     198  439.52     202  439.44     206  438.51   217.8  434.16
   221.8  433.03   229.7  431.67   233.7  431.58   281.2  433.35   332.7  436.76
#Mann= 3 ,-1 , 0
       0     .12       0   92.66    .045       0  108.52     .12       0
#XS Ineff= 2 , 0
                          133.64          431.82
Permanent Ineff=
       F       F
Bank Sta=92.66,108.52
XS Rating Curve= 0 ,0
Exp/Cntr=0.3,0.1

Type RM Length L Ch R = 1 ,1536.3  ,147.4,153.6,159.9
XS GIS Cut Line= 2
     2387560.617      387878.551     2387853.152      388099.905
#Sta/Elev= 30
       0  491.76    23.9  482.48    35.9   476.4    43.9  471.48    67.8  455.88
    75.8  449.69    79.8  446.53    87.7  436.96    91.7  433.17    95.7  430.84
    99.7  429.24   119.6  426.87  129.71424.1184   139.6  423.22  145.28424.1365
   155.5  426.24   163.5  426.92   175.4  429.07  190.05   429.7   215.3  430.41
  232.25 431.876   259.2  431.85   263.2  432.31  266.98 434.304   275.1  441.73
   287.1   455.2   291.1  458.24     307  465.15     327  472.43   366.8  484.92
#Mann= 6 ,-1 , 0
       0     .12       0  129.71    .045       0  145.28     .12       0
  190.05     .08       0  232.25    .016       0  266.98     .12       0
#XS Ineff= 2 , 0
                          158.51          428.24
Permanent Ineff=
       F       F
Bank Sta=129.71,145.28
XS Rating Curve= 0 ,0
Exp/Cntr=0.3,0.1

Type RM Length L Ch R = 1 ,1382.7  ,179,187.2,195
XS GIS Cut Line= 3
     2387488.568      387964.489     2387630.496      388150.687
     2387775.027      388253.551
#Sta/Elev= 30
       0  493.63       4  492.15    19.8  484.42    99.2  441.82   107.1  436.98
     119  427.19     123  425.15     131  424.01   134.9  422.35   138.9  420.78
   142.8  420.38   146.8  420.81   150.8  422.49  154.29 424.331   158.7  425.71
   162.7  426.14   182.5  426.71  195.83426.0277   202.4  425.32   210.3  426.16
   226.2  426.44     242  430.03   253.8  434.41   269.6  441.37   301.1  458.76
     313  464.84   344.5  479.57   368.2  489.81   391.8   496.7   411.5  499.94
#Mann= 5 ,-1 , 0
       0     .12       0   134.9    .045       0   150.8     .12       0
  154.29    .016       0  195.83     .12       0
Bank Sta=134.9,150.8
XS Rating Curve= 0 ,0
Exp/Cntr=0.3,0.1

Type RM Length L Ch R = 1 ,1195.5  ,198,199.5,202.6
XS GIS Cut Line= 3
     2387373.117      388047.822      2387456.04      388317.238
     2387470.339      388474.905
#Sta/Elev= 30
       0  473.59    47.6  444.45    51.6   442.2    79.4  430.27    87.4  423.85
    91.3  422.58   103.2   421.5   107.2  420.65  113.01418.5978   119.1   416.8
   123.1  416.73  129.13418.4077  133.63420.2138     139  422.25  160.97423.5959
   178.7  423.86   182.6  423.46  191.23421.3552   198.5  419.95   210.4   421.5
   242.2  420.69     274  422.88   325.4  424.44   349.2  426.62     361  429.46
   372.9  434.15   396.7  445.25   408.5  451.68   420.4  456.71   440.2  463.51
#Mann= 6 ,-1 , 0
       0     .12       0  113.01    .045       0  129.13     .12       0
  133.63    .016       0  160.97     .08       0  191.23     .12       0
#XS Ineff= 2 , 0
                          171.83          425.25
Permanent Ineff=
       F       F
Bank Sta=113.01,129.13
XS Rating Curve= 0 ,0
Exp/Cntr=0.3,0.1

Type RM Length L Ch R = 1 ,996.1   ,103.5,107,108.7
XS GIS Cut Line= 3
     2387166.086       388115.53     2387215.892      388203.395
      2387264.61      388506.155
#Sta/Elev= 30
       0  491.18    11.6  486.84    23.3  481.66      35  473.47    46.6  463.53
   50.91461.1418    62.2  457.75      66  455.08    93.2  430.87  102.25423.4206
     113   414.6   116.9  413.12   120.9  413.08   128.9  414.21  132.07414.8916
   152.8  422.16  161.88423.0762   188.6  424.79   192.6  424.53  201.85422.3337
   216.5  420.75   228.4  417.91   236.4  417.95   268.3  416.35   288.2  416.95
   292.2  418.47   300.1  422.83   351.9  440.29   375.8  447.62   407.6  459.33
#Mann= 8 ,-1 , 0
       0     .12       0   50.91     .06       0  102.25     .12       0
     113    .045       0   128.9     .12       0  132.07     .08       0
  161.88    .016       0  201.85     .12       0
#XS Ineff= 2 , 0
                          189.37          426.69
Permanent Ineff=
       F       F
Bank Sta=113,128.9
XS Rating Curve= 0 ,0
Exp/Cntr=0.3,0.1

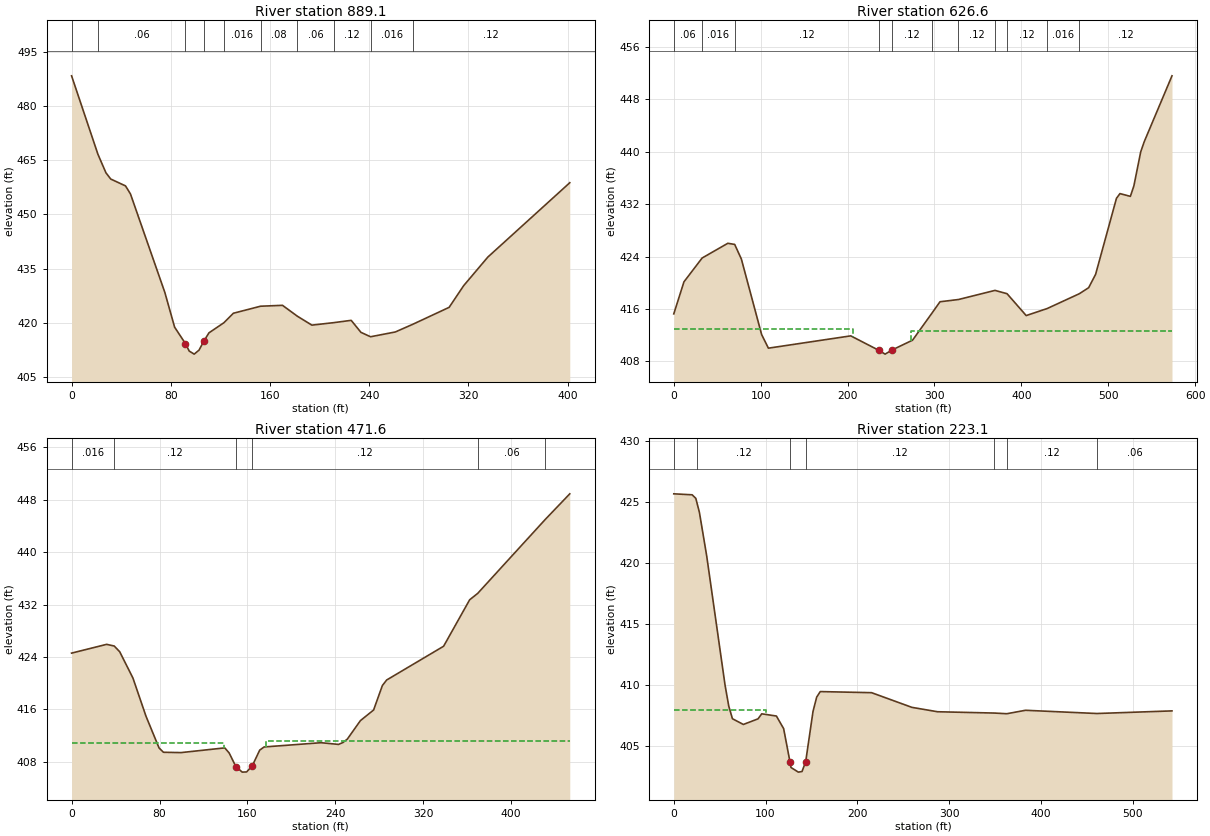
Type RM Length L Ch R = 1 ,889.1   ,307.7,262.5,222.1
XS GIS Cut Line= 3
     2387107.492      388142.874     2387131.798      388442.527
     2387166.954      388537.405
#Sta/Elev= 30
       0   488.5   21.26466.7186    27.7  461.59    31.6  459.84    43.5  457.94
    47.5   455.7    75.2  428.38    83.1  418.72    91.8  414.17    94.9  412.07
    98.9  411.23   102.8  412.34   106.8  414.91   110.8  417.14  122.84419.9444
   130.5  422.58  152.41424.5321   170.1  424.78  181.99421.7827   193.8  419.28
  211.56419.9764   225.5  420.61   233.4  417.27  241.14416.0548   261.1  417.38
  275.26419.5256   304.5  424.22   316.2  430.23   335.7  438.17   401.8  458.82
#Mann= 10 ,-1 , 0
       0     .12       0   21.26     .06       0    91.8    .045       0
   106.8     .06       0  122.84    .016       0  152.41     .08       0
  181.99     .06       0  211.56     .12       0  241.14    .016       0
  275.26     .12       0
Bank Sta=91.8,106.8
XS Rating Curve= 0 ,0
Exp/Cntr=0.3,0.1

Type RM Length L Ch R = 1 ,626.6   ,110.9,155,194.3
XS GIS Cut Line= 4
     2386790.131      388199.471     2386742.214      388301.555
      2386991.52       388363.36     2387069.298      388551.728
#Sta/Elev= 30
       0  415.24    11.7  420.13   32.61423.7687    62.2  426.02    70.1 425.849
    77.8  423.61   101.1  412.08   108.9     410   203.7  411.88   236.3  409.65
   243.2  409.09   251.3  409.73   274.8  411.22  297.04415.3322   306.4  417.09
  327.58417.4295  369.71418.8258  383.58418.3174   405.6  414.98   429.7416.0505
  466.77418.3167   477.5  419.24   485.5  421.28   509.5  432.89   513.5  433.61
   525.5  433.19   529.5  434.77   537.4  439.98   541.4  441.52   573.4   451.6
#Mann= 11 ,-1 , 0
       0     .06       0   32.61    .016       0    70.1     .12       0
   236.3    .045       0   251.3     .12       0  297.04     .06       0
  327.58     .12       0  369.71     .06       0  383.58     .12       0
   429.7    .016       0  466.77     .12       0
#XS Ineff= 2 , 0
          206.19  412.87  272.45          412.67
Permanent Ineff=
       F       F
Bank Sta=236.3,251.3
XS Rating Curve= 0 ,0
Exp/Cntr=0.3,0.1

Type RM Length L Ch R = 1 ,471.6   ,231.7,248.5,265
XS GIS Cut Line= 3
     2386697.336      388198.864     2386739.002      388534.801
     2386773.725      388644.176
#Sta/Elev= 30
       0   424.6    31.9  425.94   38.81425.6841    43.8  424.81    55.8  420.81
    67.7  414.98    79.6  410.13    83.6  409.47    99.6  409.42   139.4  410.14
   143.4  409.36   149.5  407.28   155.3  406.44   159.3  406.47   164.5  407.44
   171.2   409.8   175.2  410.28     227  410.93   242.9  410.67   246.9  410.96
   250.9  411.48   262.8   414.3   274.8  415.92   282.8  419.66   286.7   420.5
   338.5  425.65   362.2  432.74   369.5433.7137  430.83444.9727   453.3  448.91
#Mann= 6 ,-1 , 0
       0    .016       0   38.81     .12       0   149.5    .045       0
   164.5     .12       0   369.5     .06       0  430.83     .12       0
#XS Ineff= 2 , 0
           138.8  410.81  176.47          411.15
Permanent Ineff=
       F       F
Bank Sta=149.5,164.5
XS Rating Curve= 0 ,0
Exp/Cntr=0.3,0.1

Type RM Length L Ch R = 1 ,223.1   ,223.1,223.1,223.1
XS GIS Cut Line= 2
      2386581.45      388151.989     2386276.763      388601.207
#Sta/Elev= 30
       0  425.66      20  425.58      24  425.29   25.23424.9305    27.9  424.15
    35.9  420.56    55.9  409.99    59.9  408.29    63.9  407.26    75.8  406.79
    91.8  407.25    95.8  407.66   111.8  407.48   119.7  406.45  126.62403.7236
   127.7  403.27   135.7  402.89   139.7  402.94   143.7  403.74   151.7  407.86
   155.7  409.03   159.6  409.48   215.5  409.39   259.4  408.19   287.4  407.83
  349.11407.7239   362.9 407.669   383.2  407.95  461.06407.6855   542.8   407.9
#Mann= 7 ,-1 , 0
       0    .016       0   25.23     .12       0  126.62    .045       0
   143.7     .12       0  349.11     .06       0   362.9     .12       0
  461.06     .06       0
#XS Ineff= 2 , 0
          100.93  407.96
Permanent Ineff=
       F       F
Bank Sta=126.62,143.7
XS Rating Curve= 0 ,0
Exp/Cntr=0.3,0.1

Chan Stop Cuts=-1
Use User Specified Reach Order=0
Composite Channel Slope=5